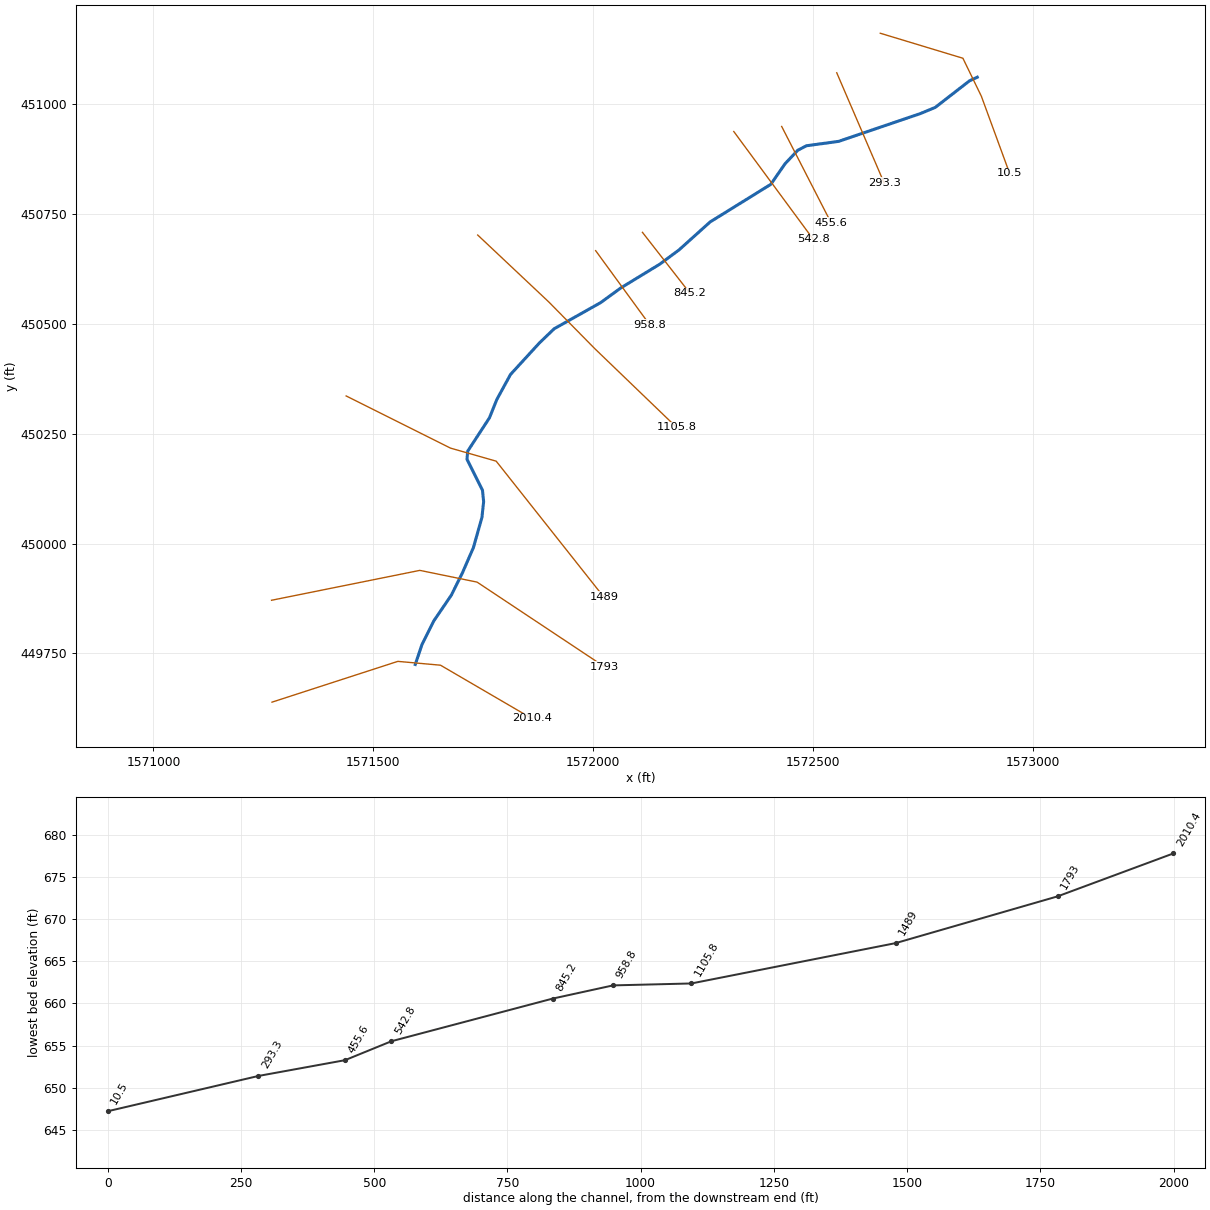
--- FRALEYFK.prj (project) ---

Proj Title=FRALEYFK
Current Plan=p01
Default Exp/Contr=0,0
English Units
Geom File=g01
Flow File=f01
Plan File=p01
BEGIN DESCRIPTION:
END DESCRIPTION:
DSS Export Rating Curves= 0
DSS Export Rating Curve Sorted= 0
DSS Export Volume Flow Curves= 0
DXF OffsetX= 0
DXF OffsetY= 0
DXF ScaleX= 0
DXF ScaleY= 0

--- FRALEYFK.p01 (plan) ---

Plan Title=Floodplain
Program Version=4.00
Geom File=g01
Flow File=f01
K Sum by GR=0
Std Step Tol=0.01
Critical Tol=0.01
Num of Std Step Trials=20
Max Error Tol=0.3
Flow Tol Ratio=0.001
Split Flow NTrial=30
Split Flow Tol=0.02
Split Flow Ratio=0.02
Log Output Level=0
Friction Slope Method=1
Unsteady Friction Slope Method=2
Unsteady Bridges Friction Slope Method=1
Global Log Level=0
CheckData=False
Run HTab=0
Run UNet=0
Run PostProcess=0
UNET Theta=0
UNET Theta Warmup=0
UNET ZTol=0
UNET ZSATol=0
UNET MxIter=0
UNET MaxInSteps=0
UNET DtIC=0
UNET DtMin=0
UNET MaxCRTS=0
UNET WFStab=0
UNET SFStab=0
UNET WFX=0
UNET SFX=0
UNET DSS MLevel=0
UNET DZMax Abort=0
UNET Convert EG Bridges=0
UNET Use Existing IB Tables=0
UNET Froude Limit=0
UNET Froude Power=0
Write IC File=0
Echo Input=False
Echo Output=False
Write Detailed=0

--- FRALEYFK.f01 (steady flow) ---

Flow Title=NFF Regression Equation
Program Version=4.00
Number of Profiles=1
Profile Names=P100yr
River Rch & RM=FRALEYFK,Main      ,2010.4
305.8458
River Rch & RM=FRALEYFK,Main      ,1793
376.1227
River Rch & RM=FRALEYFK,Main      ,293.3
399.4256
Boundary for River Rch & Prof#=FRALEYFK,Main      ,1
Up Type=0
Dn Type=3
Dn Slope=0.017357

--- FRALEYFK.g01 (geometry) ---

Geom Title=Geometry
Program Version=4.00

River Reach=FRALEYFK        ,Main
Reach XY= 30
     1571595.558       449724.91     1571610.778      449770.228
     1571637.879      449824.282     1571677.712      449882.725
     1571702.735      449933.147     1571727.768      449990.652
      1571747.14       450059.29     1571751.048      450095.314
     1571748.402        450121.3     1571713.141      450191.791
     1571714.859      450210.142     1571764.143      450285.661
     1571781.045      450327.535     1571812.185       450384.46
     1571877.832      450456.073     1571911.398      450488.357
     1572017.368      450547.953     1572062.842      450581.159
     1572151.341      450635.094     1572195.459      450667.771
     1572266.186      450731.372     1572404.228      450816.927
     1572436.614      450863.821     1572465.675      450894.464
     1572485.233      450904.613     1572558.341      450914.576
     1572743.963      450977.691      1572778.27      450991.894
     1572856.124      451052.338      1572873.63      451060.503

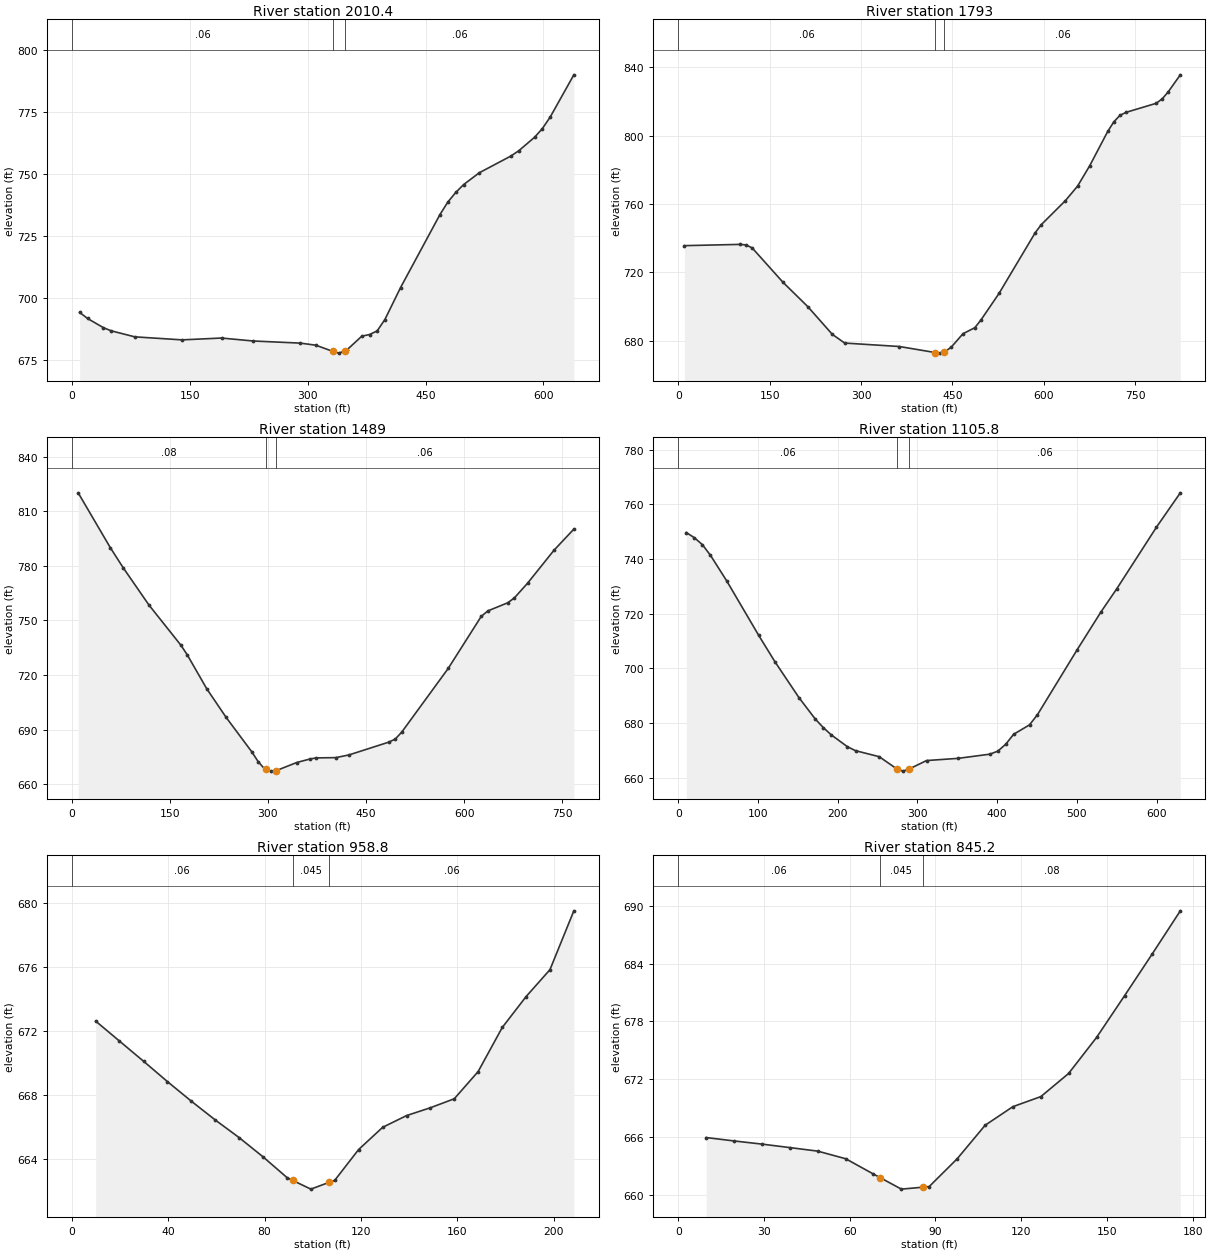
Type RM Length L Ch R = 1 ,2010.4  ,220,217.4,214.9
XS GIS Cut Line= 4
     1571269.706      449639.182     1571555.831      449731.944
     1571652.955      449723.249     1571860.651      449602.093
#Sta/Elev= 30
      10  694.26    20.1  691.79    40.1  688.11    50.1  686.82    80.2  684.38
   140.4  683.16   190.5   683.9   230.6  682.71   290.8  681.85   310.5  681.01
   332.3  678.49   339.8  677.81   347.3   678.7   349.5  678.96     369  684.66
   378.8  685.31   388.5  686.78   398.3  691.36   418.3  704.29   468.4  733.75
   478.4  738.78   488.5  742.67   498.5  745.84   518.5  750.62   558.6  757.35
   568.6  759.48   588.7  764.92   598.7  768.45   608.7  773.14   638.7  790.13
#Mann= 3 , 0 , 0
       0     .06       0   332.3    .045       0   347.3     .06       0
Bank Sta=332.3,347.3
XS Rating Curve= 0 ,0
Exp/Cntr=0.3,0.1

Type RM Length L Ch R = 1 ,1793    ,306,303.9,301.9
XS GIS Cut Line= 4
     1571268.689      449870.924     1571605.951      449938.889
       1571736.1      449912.212     1572025.297      449720.097
#Sta/Elev= 30
    10.1  735.63   101.2  736.37   111.3  736.07   121.4   734.3     172  714.16
   212.5  699.99     253  683.67   273.2  678.61     363  676.58   421.9  673.04
   429.4  672.71   436.9  673.25   448.4  676.33   467.4  684.08   486.8  687.59
   496.7  692.04   526.5  707.64     586  743.24   595.9  747.92   635.6  762.03
   655.5   770.5   675.3  782.36   705.1  802.59     715  808.11   724.9  811.89
   734.8  813.65   784.4  818.95   794.3  821.54   804.2  825.65   824.1  835.64
#Mann= 3 , 0 , 0
       0     .06       0   421.9    .045       0   436.9     .06       0
Bank Sta=421.9,436.9
XS Rating Curve= 0 ,0
Exp/Cntr=0.3,0.1

Type RM Length L Ch R = 1 ,1489    ,395,383.3,371.6
XS GIS Cut Line= 4
     1571438.394      450335.625     1571675.761      450216.942
     1571779.609      450187.271     1572024.393      449878.199
#Sta/Elev= 30
     9.8  820.15      59  789.98    78.6  778.98   117.9  758.53   167.1  736.28
   176.9   730.9   206.4  712.43   235.9  696.77   275.2   677.8     285  672.38
   294.8   668.4   297.2   668.1   304.7  667.16   312.2  667.37   343.9  671.89
   363.6  673.76   373.4  674.43   403.7  674.58   423.9  676.07   484.6  683.08
   494.7  684.79   504.8  688.73   575.6  723.62   626.1  752.22   636.2  755.24
   666.6   759.7   676.7  762.36   696.9  770.45   737.3  788.57   767.7   800.2
#Mann= 3 , 0 , 0
       0     .08       0   297.2    .045       0   312.2     .06       0
Bank Sta=297.2,312.2
XS Rating Curve= 0 ,0
Exp/Cntr=0.3,0.1

Type RM Length L Ch R = 1 ,1105.8  ,150.5,147,143.5
XS GIS Cut Line= 4
     1571737.575      450701.566     1571899.392      450549.213
     1572003.672      450443.316     1572190.056      450263.921
#Sta/Elev= 30
    10.1  749.72    20.2  747.83    30.3  745.28    40.4  741.39    60.6  732.11
     101  712.03   121.2  702.45   151.5  689.24   171.7   681.5   181.8  678.34
   191.9  675.65   212.1  671.32   222.3  669.86     252  667.66   274.2  663.17
   281.7  662.37   289.2   663.1   311.4  666.24   351.1  667.05   390.8  668.58
   400.7  669.68   410.7  672.22   420.6  675.86   440.5  679.31   450.5  683.05
   500.2  706.79   530.1  720.66     550  729.17   599.7  751.69   629.6  764.26
#Mann= 3 , 0 , 0
       0     .06       0   274.2    .045       0   289.2     .06       0
Bank Sta=274.2,289.2
XS Rating Curve= 0 ,0
Exp/Cntr=0.3,0.1

Type RM Length L Ch R = 1 ,958.8   ,112.8,113.5,114.3
XS GIS Cut Line= 2
     1572005.816      450666.006      1572128.54      450497.683
#Sta/Elev= 23
     9.9  672.63    19.8  671.38    29.8  670.12    39.7  668.85    49.6  667.63
    59.5  666.46    69.4  665.36    79.4  664.15    89.3  662.86    91.7  662.68
    99.2  662.14   106.7  662.56   109.1  662.69     119  664.61     129     666
   138.9  666.73   148.8  667.22   158.7  667.78   168.6  669.48   178.6  672.23
   188.5  674.16   198.4  675.84   208.3  679.51
#Mann= 3 , 0 , 0
       0     .06       0    91.7    .045       0   106.7     .06       0
Bank Sta=91.7,106.7
XS Rating Curve= 0 ,0
Exp/Cntr=0.3,0.1

Type RM Length L Ch R = 1 ,845.2   ,303.1,302.4,301.7
XS GIS Cut Line= 2
     1572112.214      450707.665     1572220.301      450569.178
#Sta/Elev= 20
     9.8  665.93    19.5  665.58    29.3  665.25      39  664.89    48.8  664.52
    58.6  663.73    68.3  662.14    70.6  661.77    78.1  660.57    85.6  660.77
    87.8  660.83    97.6  663.72   107.4  667.21   117.1  669.14   126.9  670.19
   136.6  672.59   146.4  676.34   156.2  680.68   165.9  685.03   175.7   689.5
#Mann= 3 , 0 , 0
       0     .06       0    70.6    .045       0    85.6     .08       0
Bank Sta=70.6,85.6
XS Rating Curve= 0 ,0
Exp/Cntr=0.3,0.1

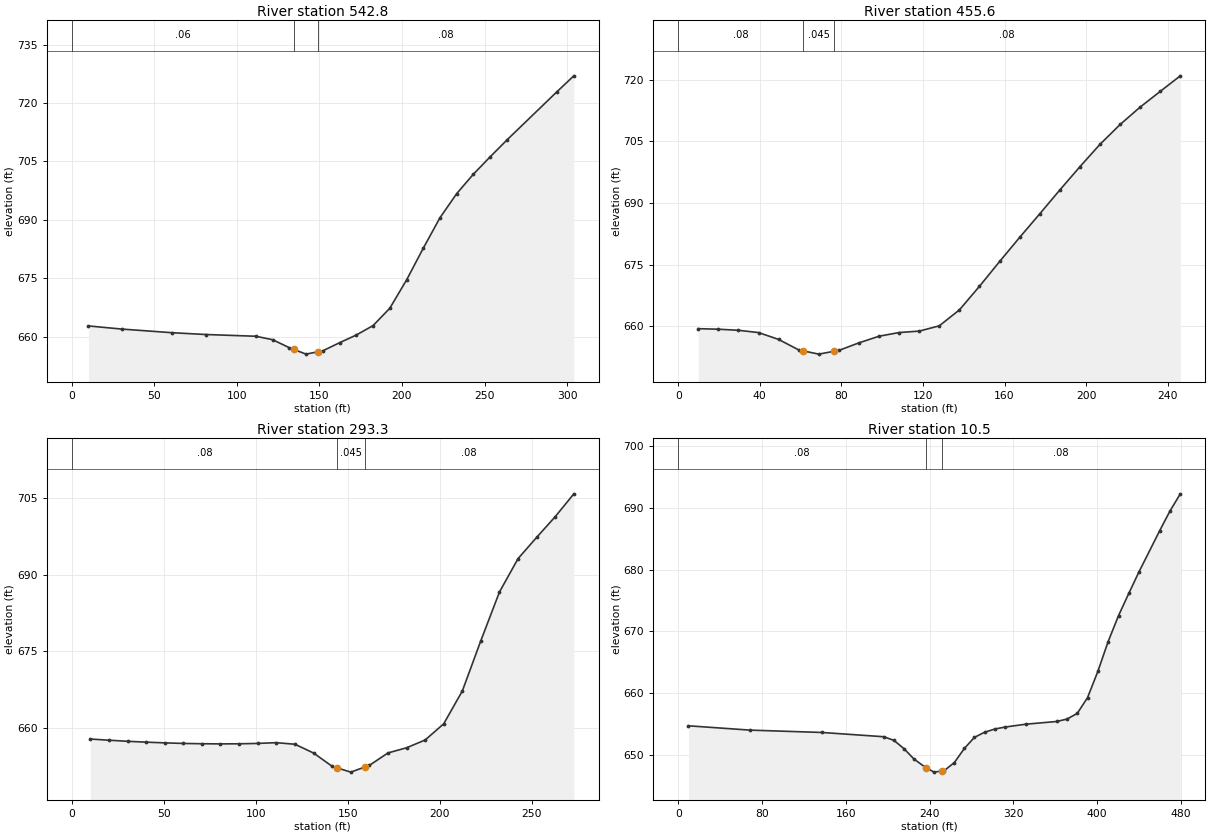
Type RM Length L Ch R = 1 ,542.8   ,91,87.2,83.4
XS GIS Cut Line= 2
     1572319.962      450936.984     1572500.459      450692.199
#Sta/Elev= 24
    10.1  662.75    30.4  661.94    60.8  661.01    81.1  660.55   111.5   660.1
   121.7  659.21   131.8  657.15   134.4  656.73   141.9  655.51   149.4  656.14
   152.1  656.37   162.2  658.44   172.3  660.41   182.5  662.84   192.6  667.28
   202.8  674.57   212.9  682.71     223  690.52   233.2  696.76   243.3  701.74
   253.4  706.17   263.6  710.52     294  722.95   304.1  726.98
#Mann= 3 , 0 , 0
       0     .06       0   134.4    .045       0   149.4     .08       0
Bank Sta=134.4,149.4
XS Rating Curve= 0 ,0
Exp/Cntr=0.3,0.1

Type RM Length L Ch R = 1 ,455.6   ,163.7,162.3,161
XS GIS Cut Line= 2
     1572428.878      450948.551     1572541.243      450729.481
#Sta/Elev= 27
     9.8  659.45    19.7  659.32    29.5  659.06    39.4   658.5    49.2  656.84
    59.1  654.28    61.4  654.04    68.9  653.26    76.4  653.95    78.8  654.17
    88.6     656    98.5  657.62   108.3  658.51   118.2  658.86     128  660.14
   137.9  664.03   147.7  669.75   157.6  675.79   167.4  681.64   177.3   687.4
   187.1  693.17     197  698.86   206.8  704.28   216.7  709.12   226.5  713.34
   236.4  717.18   246.2  720.95
#Mann= 3 , 0 , 0
       0     .08       0    61.4    .045       0    76.4     .08       0
Bank Sta=61.4,76.4
XS Rating Curve= 0 ,0
Exp/Cntr=0.3,0.1

Type RM Length L Ch R = 1 ,293.3   ,281.8,282.8,283.9
XS GIS Cut Line= 2
     1572554.105      451070.645     1572661.893      450820.019
#Sta/Elev= 29
    10.1  657.86    20.2  657.63    30.3  657.42    40.4  657.25    50.5  657.11
    60.6     657    70.7  656.94    80.8  656.91    90.9  656.93     101     657
   111.1  657.15   121.3  656.84   131.4  655.12   141.5  652.52   144.1  652.23
   151.6  651.39   159.1  652.37   161.7  652.71   171.8  655.14   181.9  656.15
     192  657.67   202.1  660.84   212.2  667.25   222.3  677.12   232.4  686.62
   242.5  693.14   252.6  697.29   262.7  701.34   272.8   705.8
#Mann= 3 , 0 , 0
       0     .08       0   144.1    .045       0   159.1     .08       0
Bank Sta=144.1,159.1
XS Rating Curve= 0 ,0
Exp/Cntr=0.3,0.1

Type RM Length L Ch R = 1 ,10.5    ,10.8,10.5,10.1
XS GIS Cut Line= 4
      1572653.14      451160.514     1572841.056      451103.644
      1572883.09      451017.104     1572947.376      450841.552
#Sta/Elev= 30
     9.8   654.7    68.7     654   137.4  653.62   196.3  652.93     206  652.34
   215.6     651   225.2  649.31   236.9  647.87   244.4   647.2   251.9  647.39
   254.1  647.45   263.7  648.75   273.3  651.04   282.9  652.83   292.5  653.65
   302.4  654.18   312.2   654.5   331.9  654.96   361.4   655.4   371.3  655.79
   381.1  656.71   390.9  659.26   400.8  663.53   410.6  668.35   420.5  672.54
   430.3  676.14   440.1  679.65   459.8  686.29   469.7   689.5   479.5  692.26
#Mann= 3 , 0 , 0
       0     .08       0   236.9    .045       0   251.9     .08       0
Bank Sta=236.9,251.9
XS Rating Curve= 0 ,0
Exp/Cntr=0.3,0.1

Chan Stop Cuts=-1
Use User Specified Reach Order=0